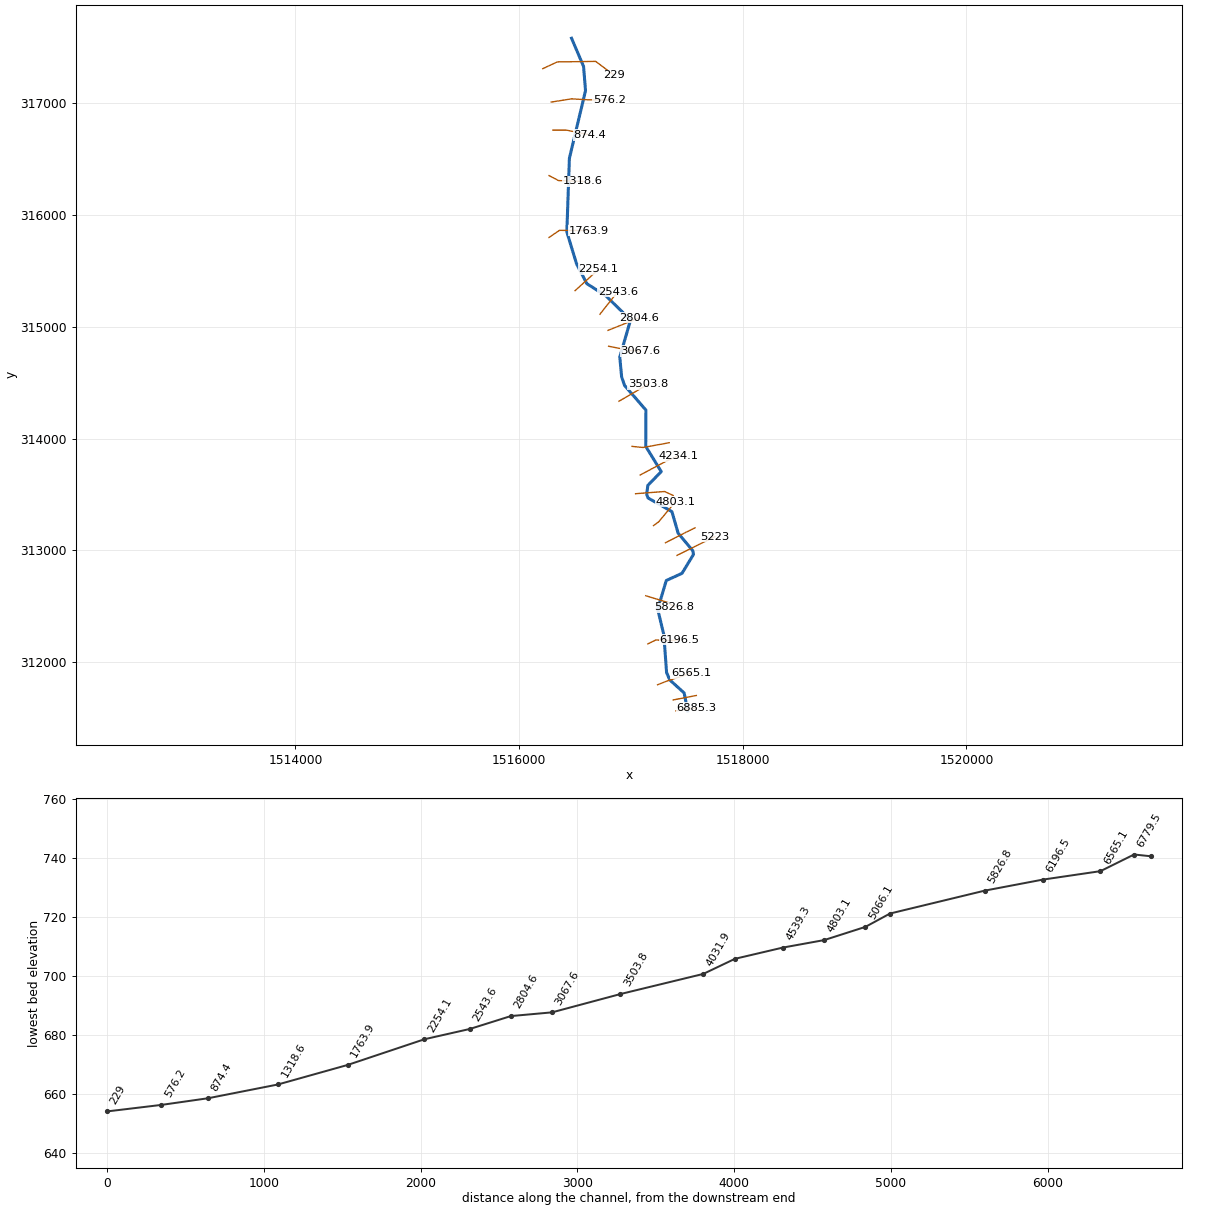
--- PantherRn.prj (project) ---

Proj Title=PantherRn
Current Plan=p01
Geom File=g01
Flow File=f01
Plan File=p01
DSS Export Rating Curves=0
DSS Export Rating Curve Sorted=0
DSS Export Volume Flow Curves=0
DXF OffsetX=0
DXF OffsetY=0
DXF ScaleX=0
DXF ScaleY=0

--- PantherRn.p01 (plan) ---

Plan Title=Floodplain
Program Version=4.00
Geom File=g01
Flow File=f01
K Sum by GR=0
Std Step Tol=0.01
Critical Tol=0.01
Num of Std Step Trials=20
Max Error Tol=0.3
Flow Tol Ratio=0.001
Split Flow NTrial=30
Split Flow Tol=0.02
Split Flow Ratio=0.02
Log Output Level=0
Friction Slope Method=1
Unsteady Friction Slope Method=2
Unsteady Bridges Friction Slope Method=1
Global Log Level=0
CheckData=False
Run HTab=0
Run UNet=0
Run PostProcess=0
UNET Theta=0
UNET Theta Warmup=0
UNET ZTol=0
UNET ZSATol=0
UNET MxIter=0
UNET MaxInSteps=0
UNET DtIC=0
UNET DtMin=0
UNET MaxCRTS=0
UNET WFStab=0
UNET SFStab=0
UNET WFX=0
UNET SFX=0
UNET DSS MLevel=0
UNET DZMax Abort=0
UNET Convert EG Bridges=0
UNET Use Existing IB Tables=0
UNET Froude Limit=0
UNET Froude Power=0
Write IC File=0
Echo Input=False
Echo Output=False
Write Detailed=0

--- PantherRn.f01 (steady flow) ---

Flow Title=NFF Regression Equation
Program Version=4.10
Number of Profiles= 1
Profile Names=P100yr
River Rch & RM=PantherRn,Main            ,6885.3
     891
River Rch & RM=PantherRn,Main            ,5066.1
     933
River Rch & RM=PantherRn,Main            ,1318.6
    1034
River Rch & RM=PantherRn,Main            ,874.4
    1249
River Rch & RM=PantherRn,Main            ,576.2
    1257
River Rch & RM=PantherRn,Main            ,229
    1259
Boundary for River Rch & Prof#=PantherRn,Main            , 1
Up Type= 0
Dn Type= 3
Dn Slope=0.00692
DSS Import GetInterval= 0
DSS Import GetPeak= 0
DSS Import FillOption= 0

--- PantherRn.g01 (geometry) ---

Geom Title=USGS 10m DEM
Program Version=4.10

River Reach=PantherRn       ,Main
Reach XY= 30
     1517507.572      311564.404     1517475.619       311725.19
     1517347.146       311841.51     1517318.579      311907.735
     1517294.077      312244.205     1517239.267      312473.219
     1517315.896      312730.399     1517456.521      312794.635
     1517558.952      312963.037     1517553.744      312996.024
     1517421.799       313154.01     1517366.244      313346.718
     1517152.939      313468.597       1517140.7      313501.149
     1517150.966      313581.093     1517270.758      313704.357
     1517132.418      313929.517     1517133.742       314254.56
     1516942.633       314475.19     1516916.591      314551.579
     1516900.062      314728.518     1516996.452       315060.26
      1516776.49      315275.684     1516605.256      315385.155
     1516513.705      315561.776     1516426.646      315847.505
     1516449.577       316506.44     1516593.674      317110.607
     1516576.313      317327.621     1516468.607      317579.873

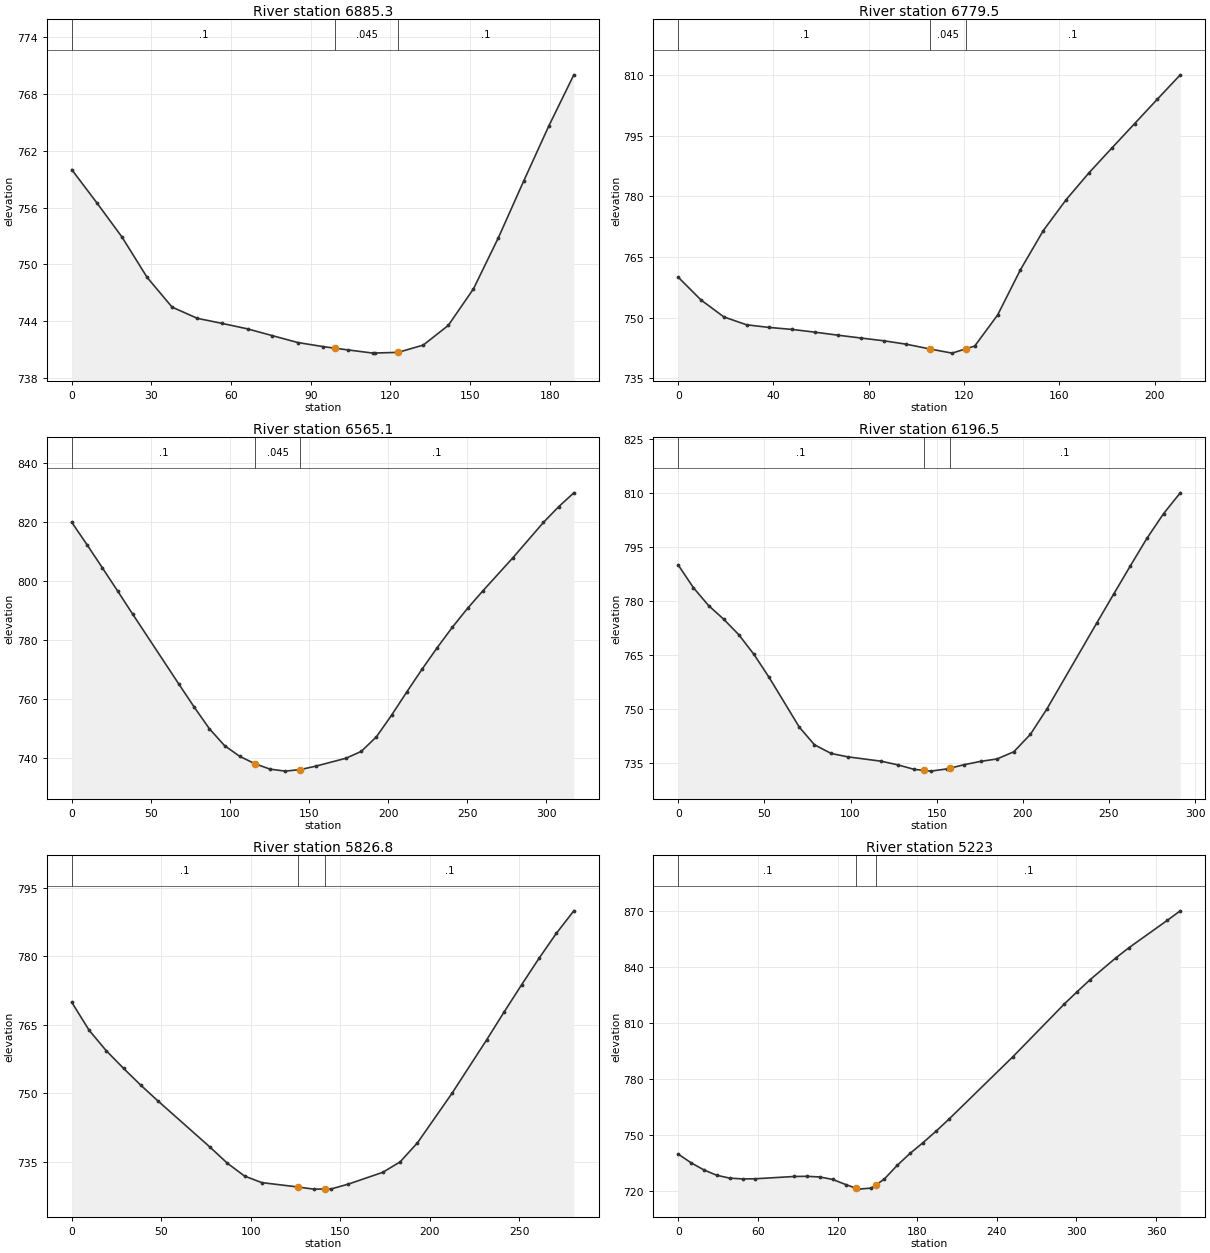
Type RM Length L Ch R = 1 ,6885.3  ,104.9,105.8,106.7
XS GIS Cut Line= 2
     1517401.029      311564.483     1517588.036      311592.521
#Sta/Elev= 23
       0     760     9.4  756.52    18.9   752.9    28.4  748.63    37.8   745.5
    47.3  744.32    56.7  743.78    66.2  743.21    75.6  742.49    85.1  741.77
    94.6  741.34    99.1  741.17     104  740.99   113.5  740.65   114.1  740.66
   122.9  740.73   132.4   741.5   141.8  743.57   151.3  747.43   160.7  752.83
   170.2  758.79   179.6  764.56   189.1     770
#Mann= 3 , 0 , 0
       0      .1       0    99.1    .045       0   122.9      .1       0
Bank Sta=99.1,122.9
XS Rating Curve= 0 ,0
Exp/Cntr=0.3,0.1

Type RM Length L Ch R = 1 ,6779.5  ,211.7,214.4,216.2
XS GIS Cut Line= 2
     1517377.731      311662.547      1517584.73      311702.223
#Sta/Elev= 25
       0     760     9.6  754.36    19.2  750.18    28.7  748.24    38.3  747.58
    47.9  747.09    57.5  746.41    67.1  745.67    76.6  744.98    86.2   744.3
    95.8  743.44   105.4   742.3   105.9  742.24     115  741.24   120.9  742.33
   124.5  742.99   134.1  750.65   143.7  761.85   153.3  771.53   162.9  779.17
   172.4  785.74     182  791.87   191.6  797.93   201.2  803.99   210.8     810
#Mann= 3 , 0 , 0
       0      .1       0   105.9    .045       0   120.9      .1       0
Bank Sta=105.9,120.9
XS Rating Curve= 0 ,0
Exp/Cntr=0.3,0.1

Type RM Length L Ch R = 1 ,6565.1  ,376.5,368.5,361.2
XS GIS Cut Line= 3
     1517237.906      311798.312     1517318.855      311830.049
     1517537.911      311901.467
#Sta/Elev= 29
       0     820     9.7  812.36    19.3   804.6      29   796.7    38.6  788.78
    67.6  765.21    77.3  757.41      87  749.98    96.6  744.25   106.2  740.61
   115.8  738.11   125.4  736.27     135   735.6   144.6  736.13   154.2  737.28
   173.4  739.98     183  742.29   192.6  747.24   202.2  754.59   211.8  762.46
   221.4  770.13     231  777.46   240.6   784.4   250.2  790.81   259.8  796.69
     279  808.05   298.2  819.97   307.8  825.28   317.4     830
#Mann= 3 , 0 , 0
       0      .1       0   115.8    .045       0   144.6      .1       0
Bank Sta=115.8,144.6
XS Rating Curve= 0 ,0
Exp/Cntr=0.3,0.1

Type RM Length L Ch R = 1 ,6196.5  ,375.6,369.8,364
XS GIS Cut Line= 4
     1517150.952      312164.113     1517222.234      312198.428
     1517357.044       312193.04     1517433.991       312201.09
#Sta/Elev= 30
       0  789.97     8.8  783.68    17.6  778.71    26.4  774.91    35.2  770.59
      44  765.12    52.7   758.8    70.3  744.94    79.1  740.04    88.8  737.63
    98.4   736.7   117.7  735.49   127.3  734.49   136.9  733.23   142.8  732.93
   146.6  732.73   156.2  733.36   157.8  733.55   165.8   734.5   175.5  735.43
   185.1  736.12   194.8  738.11   204.4  742.94     214     750     243  773.91
   252.7  781.84   262.4   789.7     272  797.33   281.7  804.22   291.4     810
#Mann= 3 , 0 , 0
       0      .1       0   142.8    .045       0   157.8      .1       0
Bank Sta=142.8,157.8
XS Rating Curve= 0 ,0
Exp/Cntr=0.3,0.1

Type RM Length L Ch R = 1 ,5826.8  ,587.6,603.8,619.8
XS GIS Cut Line= 3
      1517132.13      312594.506     1517335.288        312532.3
     1517389.887       312491.63
#Sta/Elev= 25
       0  769.96     9.7  763.83    19.3  759.33      29  755.45    38.6  751.78
    48.3  748.29    77.3   738.2    86.9   734.7    96.6  731.86   106.2  730.43
   126.4  729.47   135.2     729   141.4  729.02   144.9  729.03   154.5  730.09
   173.8  732.68   183.5  734.97   193.2  739.15   212.5     750   231.9  761.74
   241.6  767.81   251.4  773.79   261.1  779.57   270.8  785.06   280.6  790.01
#Mann= 3 , 0 , 0
       0      .1       0   126.4    .045       0   141.4      .1       0
Bank Sta=126.4,141.4
XS Rating Curve= 0 ,0
Exp/Cntr=0.3,0.1

Type RM Length L Ch R = 1 ,5223    ,156.4,156.9,157
XS GIS Cut Line= 2
     1517411.348       312955.05     1517750.315       313122.85
#Sta/Elev= 30
       0     740     9.7  735.32    19.4   731.5    29.1  728.64    38.8  727.13
    48.5  726.71    58.2  726.79    87.3     728      97   728.1   106.7  727.74
   116.4  726.43   126.1  723.72   134.2  721.66   135.8  721.25   145.5  721.82
   149.2  723.64   155.2  726.58   164.9   733.9   174.6  740.33   184.3  746.02
     194  752.07   203.7  758.48   252.2  792.08   290.9  820.24   300.6  826.83
   310.3  833.21   329.7  844.87   339.4  850.21   368.5  864.95   378.2     870
#Mann= 3 , 0 , 0
       0      .1       0   134.2    .045       0   149.2      .1       0
Bank Sta=134.2,149.2
XS Rating Curve= 0 ,0
Exp/Cntr=0.3,0.1

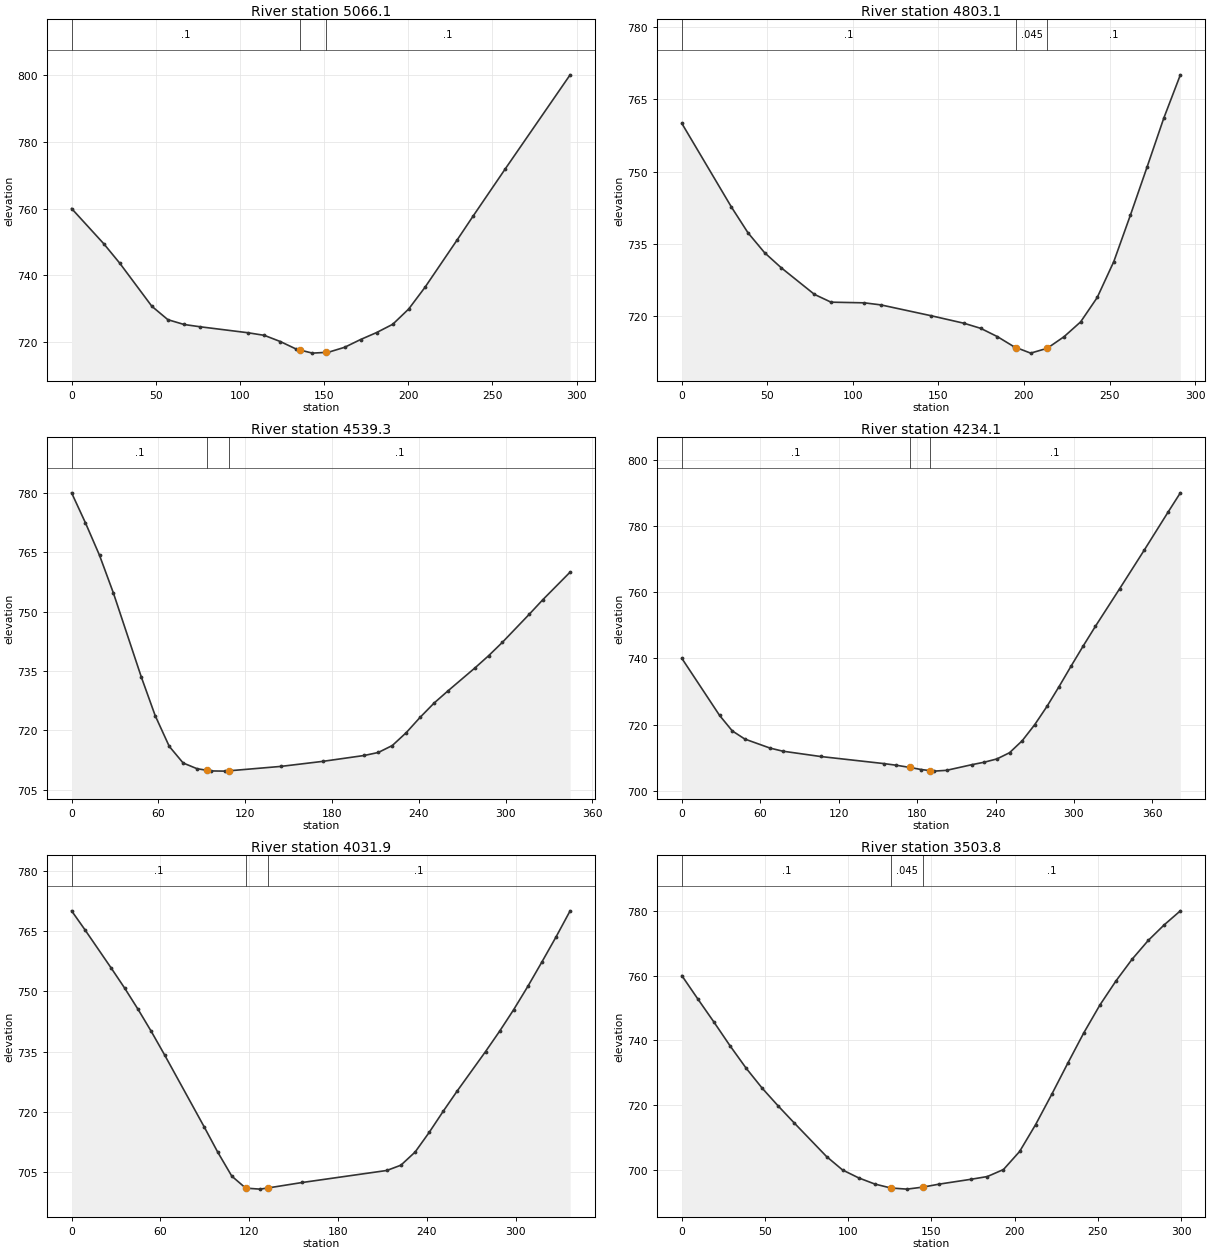
Type RM Length L Ch R = 1 ,5066.1  ,253.8,263,272
XS GIS Cut Line= 3
     1517308.316      313067.925     1517486.605      313159.214
     1517572.598       313201.59
#Sta/Elev= 25
       0     760    19.1  749.47    28.6  743.65    47.7  730.74    57.2  726.74
    66.8   725.3    76.3  724.62   104.9  722.82   114.5  722.05     124   720.2
   133.5  717.93   135.9  717.63   143.1  716.73   150.9  716.95   152.6     717
   162.2  718.47   171.7   720.8   181.2  722.88   190.8  725.36   200.3  729.94
   209.9  736.38   229.1  750.62   238.6  757.77   257.8  771.96   296.2     800
#Mann= 3 , 0 , 0
       0      .1       0   135.9    .045       0   150.9      .1       0
Bank Sta=135.9,150.9
XS Rating Curve= 0 ,0
Exp/Cntr=0.3,0.1

Type RM Length L Ch R = 1 ,4803.1  ,283,263.8,244.4
XS GIS Cut Line= 3
     1517201.559      313221.275     1517248.375      313255.628
     1517397.942      313434.723
#Sta/Elev= 25
       0     760      29  742.61    38.7  737.25    48.4  733.12    58.1     730
    77.5  724.47    87.2  722.85   106.7  722.71   116.4  722.28   145.6  720.04
     165  718.46   174.7  717.41   184.5  715.68   194.2  713.58   195.6  713.39
   203.9  712.26   213.6  713.27   223.4  715.67   233.1  718.75   242.8  723.82
   252.5  731.29   262.2  740.94     272  750.99   281.7  761.08   291.4  770.09
#Mann= 3 , 0 , 0
       0      .1       0   195.6    .045       0   213.6      .1       0
Bank Sta=195.6,213.6
XS Rating Curve= 0 ,0
Exp/Cntr=0.3,0.1

Type RM Length L Ch R = 1 ,4539.3  ,295.3,305.2,315.1
XS GIS Cut Line= 3
     1517041.317      313506.707     1517300.778      313526.392
     1517377.378      313490.988
#Sta/Elev= 28
       0     780     9.6   772.4    19.3  764.22    28.9   754.7    48.2  733.48
    57.8  723.72    67.5  715.98    77.1  711.78    86.7  710.33    93.8  709.92
    96.4  709.77     106  709.72   108.8   709.8   144.6  710.91   173.5  712.18
   202.4  713.68     212  714.43   221.7  716.19   231.3  719.43   240.9   723.3
   250.6  726.92   260.2     730     279  735.84   288.3  738.88   297.7  742.22
   316.5  749.39   325.8  753.04   344.6  759.98
#Mann= 3 , 0 , 0
       0      .1       0    93.8    .045       0   108.8      .1       0
Bank Sta=93.8,108.8
XS Rating Curve= 0 ,0
Exp/Cntr=0.3,0.1

Type RM Length L Ch R = 1 ,4234.1  ,209,202.1,195.2
XS GIS Cut Line= 3
     1517082.439       313674.03     1517320.942      313800.636
     1517423.486      313844.125
#Sta/Elev= 29
       0     740    28.9  722.74    38.6  718.07    48.2  715.61    67.5  712.88
    77.2  711.95   106.1  710.34   154.3  708.21   163.9  707.71   174.7  707.02
   183.2   706.4   189.7  706.08   192.9  705.92   202.5  706.16   221.8  707.86
   231.4  708.62   241.1  709.61   250.7  711.48   260.4   715.1     270  719.97
   279.3  725.45   288.6  731.46   297.9  737.72   307.2  743.82   316.4  749.67
     335  761.06   353.6  772.59   372.1  784.24   381.4     790
#Mann= 3 , 0 , 0
       0      .1       0   174.7    .045       0   189.7      .1       0
Bank Sta=174.7,189.7
XS Rating Curve= 0 ,0
Exp/Cntr=0.3,0.1

Type RM Length L Ch R = 1 ,4031.9  ,519.9,528.1,535.6
XS GIS Cut Line= 3
     1517009.591      313929.935     1517107.776      313920.092
     1517341.974      313962.433
#Sta/Elev= 27
       0     770       9   765.3    26.9  755.69    35.9  750.75    44.8  745.56
    53.8  740.03    62.8  734.18    89.7  716.18    98.7     710   108.2  704.03
   117.6  701.05   127.2   700.8   132.6  701.09   155.8  702.45   212.9  705.44
   222.4  706.75     232  710.02   241.5   714.9     251  720.17   260.5  725.24
   279.6  735.02   289.1  740.08   298.6  745.44   308.1  751.19   317.6  757.26
   327.2  763.52   336.7     770
#Mann= 3 , 0 , 0
       0      .1       0   117.6    .045       0   132.6      .1       0
Bank Sta=117.6,132.6
XS Rating Curve= 0 ,0
Exp/Cntr=0.3,0.1

Type RM Length L Ch R = 1 ,3503.8  ,452.8,436.2,420.2
XS GIS Cut Line= 2
     1516892.853      314333.477      1517151.63      314484.451
#Sta/Elev= 30
       0     760     9.7  752.71    19.3  745.63      29  738.28    38.7  731.34
    48.3  725.19      58  719.65    67.6  714.42      87  704.05    96.6  699.91
   106.3  697.46     116  695.56   125.6  694.34   135.3  693.99     145  694.62
   154.6  695.53     174  697.05   183.6  697.88   193.3  700.05     203  705.63
   212.6  713.93   222.3  723.29     232  732.97   241.6  742.33   251.3  750.95
   260.9  758.35   270.6  765.06   280.3  770.87   289.9  775.69   299.6  780.02
#Mann= 3 , 0 , 0
       0      .1       0   125.6    .045       0     145      .1       0
Bank Sta=125.6,145
XS Rating Curve= 0 ,0
Exp/Cntr=0.3,0.1

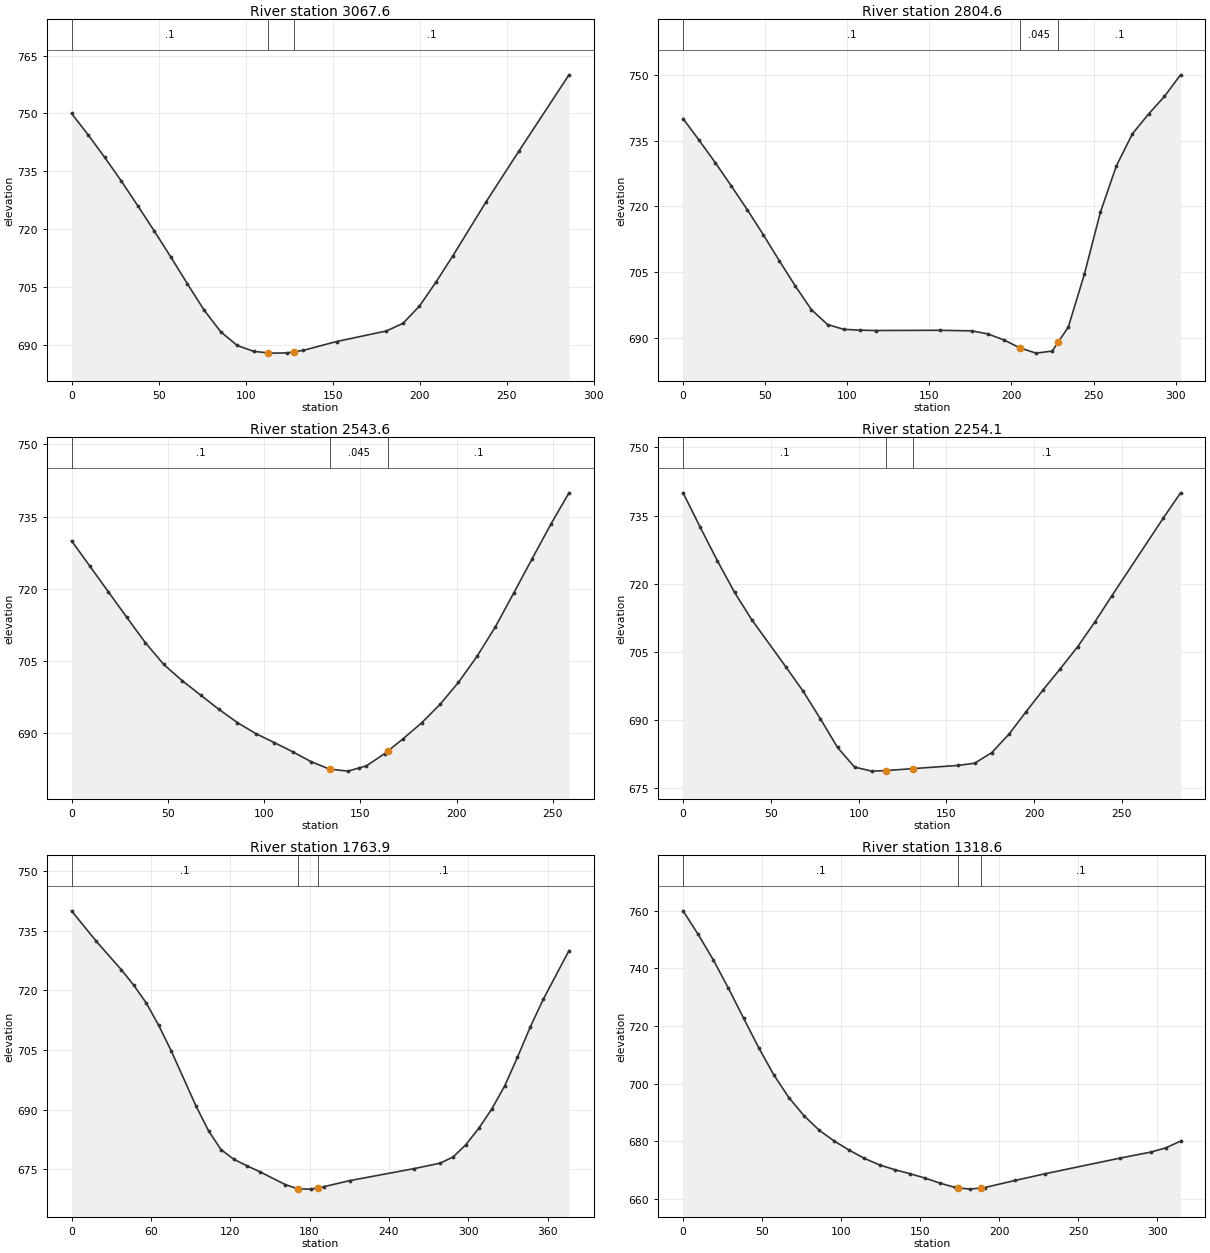
Type RM Length L Ch R = 1 ,3067.6  ,249.7,262.9,276
XS GIS Cut Line= 3
     1516800.319      314825.285     1516996.534      314787.184
     1517082.287       314782.45
#Sta/Elev= 26
       0  749.99     9.5  744.45      19  738.62    28.6  732.44    38.1  726.01
    47.6  719.43    57.1  712.68    66.6  705.75    76.1     699    85.7  693.34
    95.2  689.77   104.7  688.25     113  687.85   114.2  687.79   123.7  687.84
     128  688.15   133.2  688.52   152.3   690.8   180.8  693.53   190.4  695.51
   199.9     700   209.4  706.24     219  712.98     238  726.94   257.1  740.26
   285.8     760
#Mann= 3 , 0 , 0
       0      .1       0     113    .045       0     128      .1       0
Bank Sta=113,128
XS Rating Curve= 0 ,0
Exp/Cntr=0.3,0.1

Type RM Length L Ch R = 1 ,2804.6  ,249.4,261.1,272.9
XS GIS Cut Line= 2
     1516794.861      314967.465     1517076.226      315079.965
#Sta/Elev= 29
       0     740     9.8  735.06    19.6  729.99    29.3   724.7    39.1  719.24
    48.9  713.51    58.6  707.61    68.4  701.81    78.2  696.43      88  693.05
    97.8  691.96   107.5  691.77   117.3  691.69   156.4  691.74     176  691.61
   185.7   690.9   195.5  689.53   205.3  687.69     215  686.53   224.8     687
   228.6  689.11   234.6  692.44   244.4   704.5   254.2  718.69   263.9  729.21
   273.7  736.56   283.5  741.05   293.2  745.08     303     750
#Mann= 3 , 0 , 0
       0      .1       0   205.3    .045       0   228.6      .1       0
Bank Sta=205.3,228.6
XS Rating Curve= 0 ,0
Exp/Cntr=0.3,0.1

Type RM Length L Ch R = 1 ,2543.6  ,293.2,289.5,285.8
XS GIS Cut Line= 2
     1516722.483      315111.622     1516882.709      315314.395
#Sta/Elev= 30
       0     730     9.6   724.7    19.1  719.41    28.7  714.11    38.3  708.87
    47.9  704.32    57.4  700.98      67  697.98    76.6  694.98    86.2  692.24
    95.7  689.97   105.3   688.1   114.9  686.19   124.4  684.14     134  682.59
   143.6  682.17   149.2  682.81   153.2  683.27   162.7  685.82   164.2   686.3
   172.3  688.92   181.9  692.21   191.4  696.03     201  700.61   210.6     706
   220.2  712.16   229.7  719.16   239.3  726.31   248.9   733.4   258.4  739.96
#Mann= 3 , 0 , 0
       0      .1       0     134    .045       0   164.2      .1       0
Bank Sta=134,164.2
XS Rating Curve= 0 ,0
Exp/Cntr=0.3,0.1

Type RM Length L Ch R = 1 ,2254.1  ,506.9,490.1,473.1
XS GIS Cut Line= 2
     1516500.127      315322.336     1516710.128      315512.651
#Sta/Elev= 25
       0     740     9.8   732.4    19.6  724.99    29.3  718.09    39.1  712.06
    58.6  701.64    68.4  696.29    78.2  690.23      88   683.9    97.7  679.58
   107.5  678.69   115.8  678.82   130.8  679.24   156.4  679.94   166.1  680.43
   175.9  682.78   185.7  686.85   195.4  691.78   205.2  696.64     215  701.29
   224.8  706.11   234.5   711.5   244.3  717.34   273.6  734.46   283.4     740
#Mann= 3 , 0 , 0
       0      .1       0   115.8    .045       0   130.8      .1       0
Bank Sta=115.8,130.8
XS Rating Curve= 0 ,0
Exp/Cntr=0.3,0.1

Type RM Length L Ch R = 1 ,1763.9  ,445.8,445.3,444.6
XS GIS Cut Line= 3
     1516266.953      315797.822     1516360.222      315861.563
     1516623.471      315859.739
#Sta/Elev= 30
       0  740.01    18.8  732.32    37.7  725.17    47.1  721.27    56.5  716.82
    65.9   711.2    75.3  704.84    94.1  690.91   103.6  684.67     113  679.93
   122.7   677.5   132.5  675.87   142.2  674.39   161.7  671.11   171.2  670.06
   181.2  669.98   186.2   670.3     191  670.61   210.5  672.13   259.2  675.15
   278.7  676.51   288.5  678.06   298.2  681.16     308   685.3   317.7  690.09
   327.5  695.91   337.2  703.15     347  710.85   356.7  717.73   376.2     730
#Mann= 3 , 0 , 0
       0      .1       0   171.2    .045       0   186.2      .1       0
Bank Sta=171.2,186.2
XS Rating Curve= 0 ,0
Exp/Cntr=0.3,0.1

Type RM Length L Ch R = 1 ,1318.6  ,448.1,444.3,440.4
XS GIS Cut Line= 3
     1516267.955       316351.19     1516352.855      316306.846
     1516571.778      316299.497
#Sta/Elev= 29
       0     760     9.6  751.78    19.2   742.9    28.7  733.12    38.3  722.72
    47.9  712.43    57.5  702.96      67   695.1    76.6  688.82    86.2  683.78
    95.8     680   105.3  676.84   114.8  674.02   124.4  671.75   133.9  670.12
   143.4  668.74   152.9  667.24   162.4  665.48     172  663.95   173.7  663.84
   181.5  663.36   188.7  663.78     191  663.92   210.1  666.38   229.1   668.7
   276.7  674.16   295.8   676.2   305.3  677.65   314.8  680.04
#Mann= 3 , 0 , 0
       0      .1       0   173.7    .045       0   188.7      .1       0
Bank Sta=173.7,188.7
XS Rating Curve= 0 ,0
Exp/Cntr=0.3,0.1

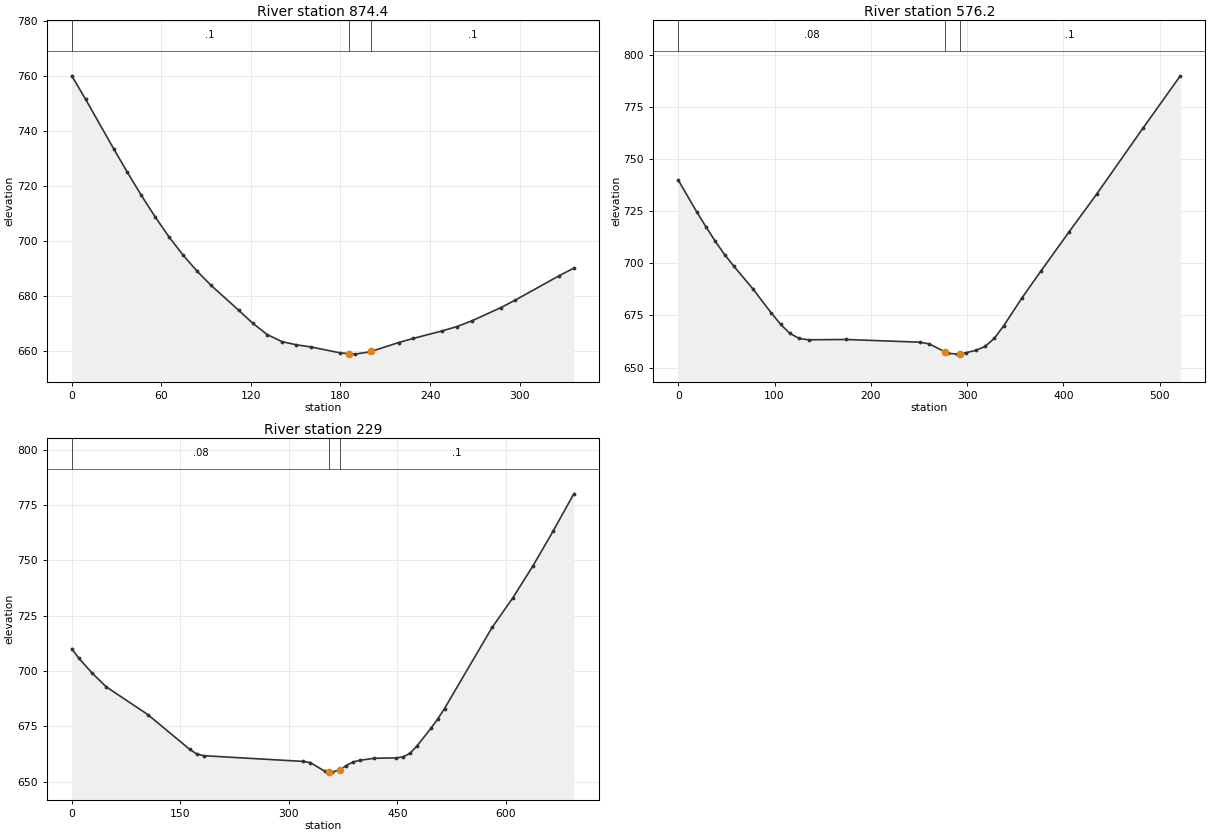
Type RM Length L Ch R = 1 ,874.4   ,294.8,298.2,301.7
XS GIS Cut Line= 3
     1516301.984      316758.048     1516423.125      316758.228
     1516633.886      316714.789
#Sta/Elev= 30
       0  759.98     9.3  751.42      28  733.51    37.3  724.84    46.6  716.48
    55.9  708.62    65.2  701.32    74.6  694.73    83.9  688.92    93.2  683.79
   111.8  674.68   121.1  670.01   130.9  665.83   140.7  663.27   150.5   662.1
   160.3  661.31   179.8  659.16   185.5   658.9   189.6  658.71   199.4  659.51
   200.5   659.7     219  662.93   228.7  664.42   248.3  667.19   258.1  668.76
   267.9   670.8   287.4  675.64   297.2  678.41   326.6  687.28   336.3  690.01
#Mann= 3 , 0 , 0
       0      .1       0   185.5    .045       0   200.5      .1       0
Bank Sta=185.5,200.5
XS Rating Curve= 0 ,0
Exp/Cntr=0.3,0.1

Type RM Length L Ch R = 1 ,576.2   ,346,347.1,348.4
XS GIS Cut Line= 4
     1516286.916      317008.727     1516468.226      317037.667
     1516622.181      317029.032     1516805.687      317025.531
#Sta/Elev= 30
       0  739.98    19.3  724.63      29   717.4    38.6   710.5    48.3  704.14
      58  698.51    77.3   687.9    96.6   676.2   106.3  670.77     116  666.37
   125.6  663.96   135.3  663.33   173.9  663.48   251.1  662.18   260.7  661.35
   277.2  657.49     280  656.87   289.6  656.45   292.2  656.65   299.2  657.18
   308.9  658.24   318.5  660.13   328.2  664.02   337.8  669.96   357.1  683.57
   376.4   696.2   405.4  714.88   434.4   733.2   482.7     765   521.3     790
#Mann= 3 , 0 , 0
       0     .08       0   277.2    .045       0   292.2      .1       0
Bank Sta=277.2,292.2
XS Rating Curve= 0 ,0
Exp/Cntr=0.3,0.1

Type RM Length L Ch R = 1 ,229     ,217.9,229,239.9
XS GIS Cut Line= 4
     1516211.404      317307.231     1516341.052       317367.98
     1516684.659      317372.676     1516849.849      317248.161
#Sta/Elev= 30
       0  709.97     9.5  705.82    28.6  698.83    47.7  692.76     105  680.27
   162.8  664.58   172.6  662.47   182.4  661.66   319.9  659.08   329.7  658.54
   349.4  654.67   355.7  654.39   359.2  654.24   370.7  655.32   378.8  657.15
   388.6  658.82   398.4  659.61   418.1   660.5   447.5  660.65   457.4  661.11
   467.2  662.71     477  666.07   496.2  674.02   505.6  678.24     515  682.97
   580.8  719.65     609   732.8   637.3   747.5   665.5  763.42   693.7     780
#Mann= 3 , 0 , 0
       0     .08       0   355.7    .045       0   370.7      .1       0
Bank Sta=355.7,370.7
XS Rating Curve= 0 ,0
Exp/Cntr=0.3,0.1

Chan Stop Cuts=-1
Use User Specified Reach Order=0
Composite Channel Slope=5